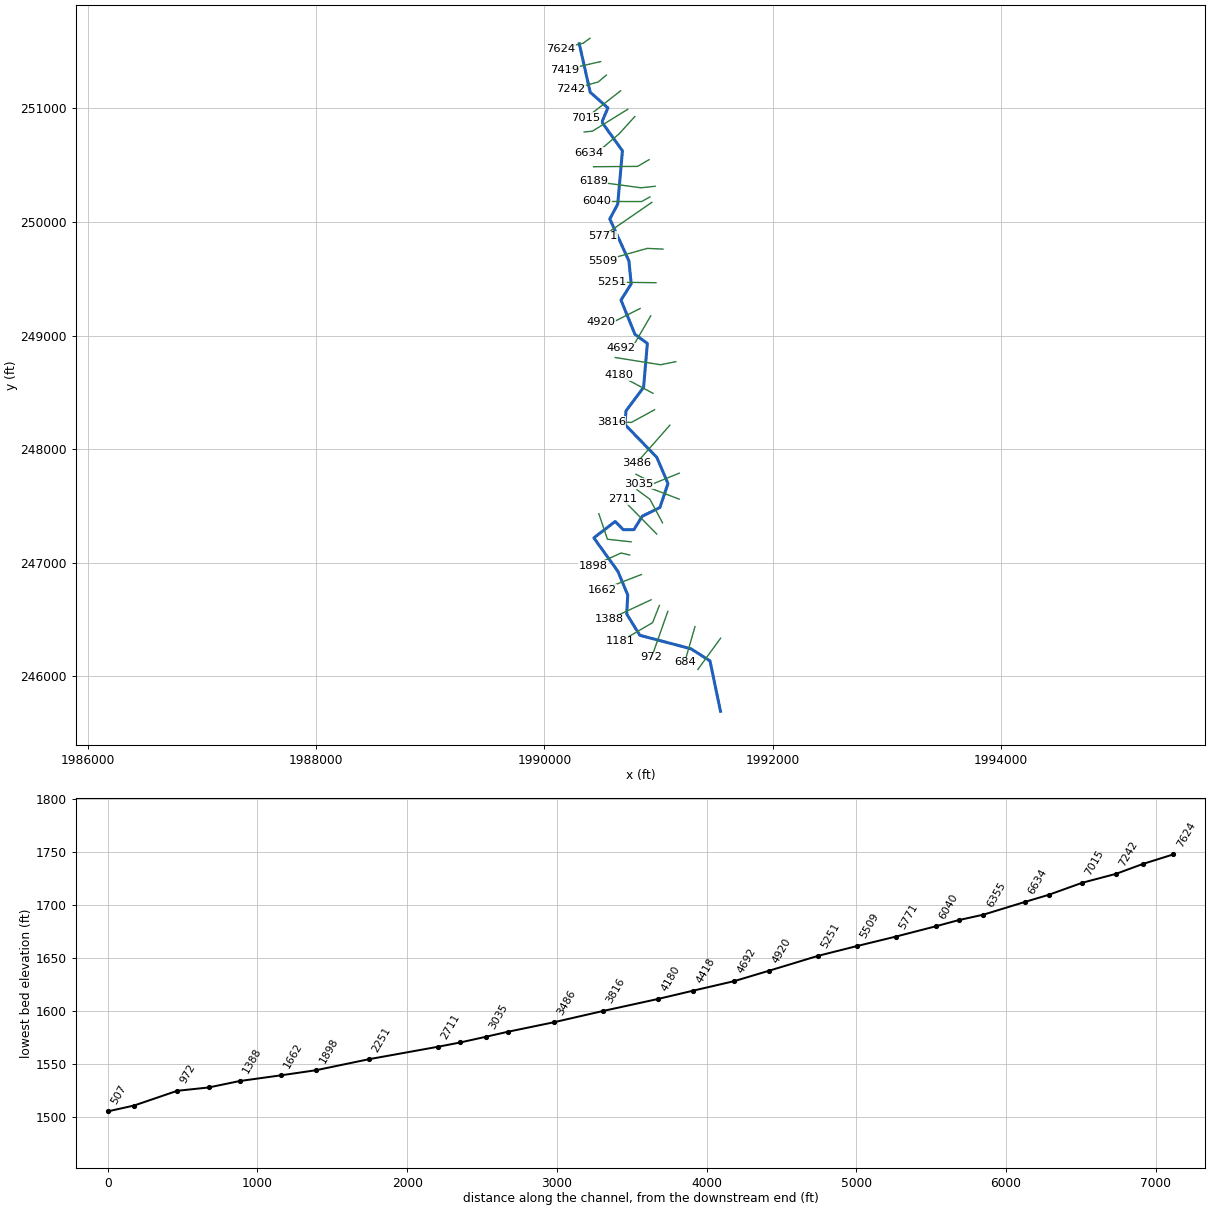
--- RFKMADAMCK.prj (project) ---

Proj Title=RFKMADAMCK
Current Plan=p01
Default Exp/Contr=0,0
English Units
Geom File=g01
Flow File=f01
Plan File=p01
BEGIN DESCRIPTION:
Stream Name: Righthand Fork Madam Creek
Flood Zone: Approximate
Summers County, West Virginia
HEC-RAS Version: 5.0.7
Hydrology Method:
regression
Model Notes:
END DESCRIPTION:
DSS Export Rating Curves= 0
DSS Export Rating Curve Sorted= 0
DSS Export Volume Flow Curves= 0
DXF OffsetX= 0
DXF OffsetY= 0
DXF ScaleX= 0
DXF ScaleY= 0

--- RFKMADAMCK.p01 (plan) ---

Plan Title=Floodplain
Program Version=5.07
Short Identifier=Floodplain
Geom File=g01
Flow File=f01
Subcritical Flow
K Sum by GR= 0
Std Step Tol= 0.01
Critical Tol= 0.01
Num of Std Step Trials= 20
Max Error Tol= 0.3
Flow Tol Ratio= 0.001
Split Flow NTrial= 30
Split Flow Tol= 0.02
Split Flow Ratio= 0.02
Log Output Level= 0
Friction Slope Method= 1
Unsteady Friction Slope Method= 2
Unsteady Bridges Friction Slope Method= 1
Parabolic Critical Depth
Global Vel Dist= 0 , 0 , 0
Global Log Level= 0
CheckData=True
Encroach Param=-1 ,0,0, 0
Mapping Interval=1HOUR
Computation Time Step Use Courant=        0
Computation Time Step Use Time Series=    0
Computation Time Step Count To Double=0
Computation Time Step Max Doubling=0
Computation Time Step Max Halving=0
Computation Time Step Residence Courant=0
Run HTab= 0
Run UNet= 0
Run Sediment= 0
Run PostProcess= 0
Run WQNet= 0
Run RASMapper= 0
UNET Theta= 0
UNET Theta Warmup= 0
UNET ZTol= 0
UNET ZSATol= 0
UNET MxIter= 0
UNET Max Iter WO Improvement= 0
UNET MaxInSteps= 0
UNET DtIC= 0
UNET DtMin= 0
UNET MaxCRTS= 0
UNET WFStab= 0
UNET SFStab= 0
UNET WFX= 1
UNET SFX= 1
UNET 1D Methodology=Finite Difference
UNET DSS MLevel= 1
UNET Pardiso=0
UNET DZMax Abort= 0
UNET Use Existing IB Tables= 0
UNET Froude Reduction=False
UNET Froude Limit= 0
UNET Froude Power= 0
UNET D1 Cores= 0
UNET D2 Coriolis=0
UNET D2 Cores= 0
UNET D2 Theta= 1
UNET D2 Theta Warmup= 1
UNET D2 Z Tol= 0.01
UNET D2 Volume Tol= 0.01
UNET D2 Max Iterations= 20
UNET D2 Equation= 0
UNET D2 RampUpFraction=0.1
UNET D2 TimeSlices= 1
UNET D2 BCVolumeCheck=0
UNET D1D2 MaxIter= 0
UNET D1D2 ZTol=0.01
UNET D1D2 QTol=0.1
UNET D1D2 MinQTol=1
Write IC File= 0
Write IC File at Fixed DateTime=0
Write IC File at Sim End=0
Echo Input=False
Echo Parameters=False
Echo Output=False
Write Detailed= 0
HDF Write Warmup=0
HDF Write Time Slices=0
HDF Flush=0
HDF Face Node Velocities=0
HDF Compression= 1
HDF Chunk Size= 1
HDF Spatial Parts= 1
HDF Use Max Rows=0
HDF Fixed Rows= 1
Calibration Method= 0
Calibration Iterations= 20
Calibration Max Change=0.05
Calibration Tolerance=0.2
Calibration Maximum=1.5
Calibration Minimum=0.5
Calibration Optimization Method= 1
WQ AD Non Conservative
WQ ULTIMATE=-1
WQ Max Comp Step=1HOUR
WQ Output Interval=15MIN
WQ Output Selected Increments= 0
WQ Output face flow=0
WQ Output face velocity=0
WQ Output face area=0
WQ Output face dispersion=0
WQ Output cell volume=0
WQ Output cell surface area=0
WQ Output cell continuity=0
WQ Output cumulative cell continuity=0
WQ Output face conc=0
WQ Output face dconc_dx=0
WQ Output face courant=0
WQ Output face peclet=0
WQ Output face adv mass=0
WQ Output face disp mass=0
WQ Output cell mass=0
WQ Output cell source sink temp=0
WQ Output nsm pathways=0
WQ Output nsm derived pathways=0
WQ Output MaxMinRange=-1
WQ Daily Max Min Mean=-1
WQ Daily Range=0
WQ Daily Time=0
WQ Create Restart=0
WQ Fixed Restart=0
WQ System Summary=0
WQ Write To DSS=0
WQ Use Fixed Temperature=0
Sorting and Armoring Iterations= 10
XS Update Threshold= 0.02
Bed Roughness Predictor= 0
Hydraulics Update Threshold= 0.02
Energy Slope Method= 1
Volume Change Method= 1
Sediment Retention Method= 0
XS Weighting Method= 0
Number of US Weighted Cross Sections= 1
Number of DS Weighted Cross Sections= 1
Upstream XS Weight=0
Main XS Weight=1
Downstream XS Weight=0
Number of DS XS's Weighted with US Boundary= 1
Upstream Boundary Weight= 1
Weight of XSs Associated with US Boundary= 0
Number of US XS's Weighted with DS Boundary= 1
Downstream Boundary Weight= 0.5
Weight of XSs Associated with DS Boundary= 0.5
Percentile Method= 0
Sediment Output Level= 3
Mass or Volume Output= 0
Output Increment Type= 1
Profile and TS Output Increment= 1
XS Output Flag= 0
XS Output Increment= 10
Write Gradation File= 0
Read Gradation Hotstart= 0
Write HDF5 File= 1
Write Binary Output= 1
Write DSS Sediment File= 0
SV Curve= 0
Specific Gage Flag= 0

--- RFKMADAMCK.f01 (steady flow) ---

Flow Title=Flows
Program Version=5.07
Number of Profiles= 6
Profile Names=01pct,10pct,04pct,02pct,0_2pct,01plus
River Rch & RM=RFKMADAMCK,Main            ,7624
     620     329     436     525     865     917
River Rch & RM=RFKMADAMCK,Main            ,2251
     699     372     493     593     972    1033
Boundary for River Rch & Prof#=RFKMADAMCK,Main            , 1
Up Type= 0
Dn Type= 3
Dn Slope=0.029812
Boundary for River Rch & Prof#=RFKMADAMCK,Main            , 2
Up Type= 0
Dn Type= 3
Dn Slope=0.029812
Boundary for River Rch & Prof#=RFKMADAMCK,Main            , 3
Up Type= 0
Dn Type= 3
Dn Slope=0.029812
Boundary for River Rch & Prof#=RFKMADAMCK,Main            , 4
Up Type= 0
Dn Type= 3
Dn Slope=0.029812
Boundary for River Rch & Prof#=RFKMADAMCK,Main            , 5
Up Type= 0
Dn Type= 3
Dn Slope=0.029812
Boundary for River Rch & Prof#=RFKMADAMCK,Main            , 6
Up Type= 0
Dn Type= 3
Dn Slope=0.029812
DSS Import GetInterval= 0
DSS Import GetPeak= 0
DSS Import FillOption= 0

--- RFKMADAMCK.g01 (geometry) ---

Geom Title=Geometry
Program Version=5.07

River Reach=RFKMADAMCK      ,Main
Reach XY= 30
     1990305.817      251568.691     1990401.705      251141.984
 1990556.5658211251004.039578358     1990504.081      250879.001
1990684.24393937      250626.223      1990642.97      250157.474
     1990573.525      250026.397     1990740.883      249657.632
     1990761.025      249455.2161990671.66706343249312.797652985
1990793.98631981249010.663299584     1990902.518      248930.911
     1990869.615      248544.808     1990715.448      248337.169
     1990707.115      248216.336     1990985.415      247928.205
     1991083.331      247697.736     1991012.724      247486.528
     1990857.809      247410.086     1990784.893       247292.03
     1990691.143       247292.03     1990620.309      247363.558
1990433.48906647      247219.114     1990643.684       246926.26
     1990730.726      246717.0371990721.68837765246549.410236665
     1990836.281      246362.1691991284.88768882246243.169859018
1991451.68249232 246136.50241786     1991543.651      245693.672

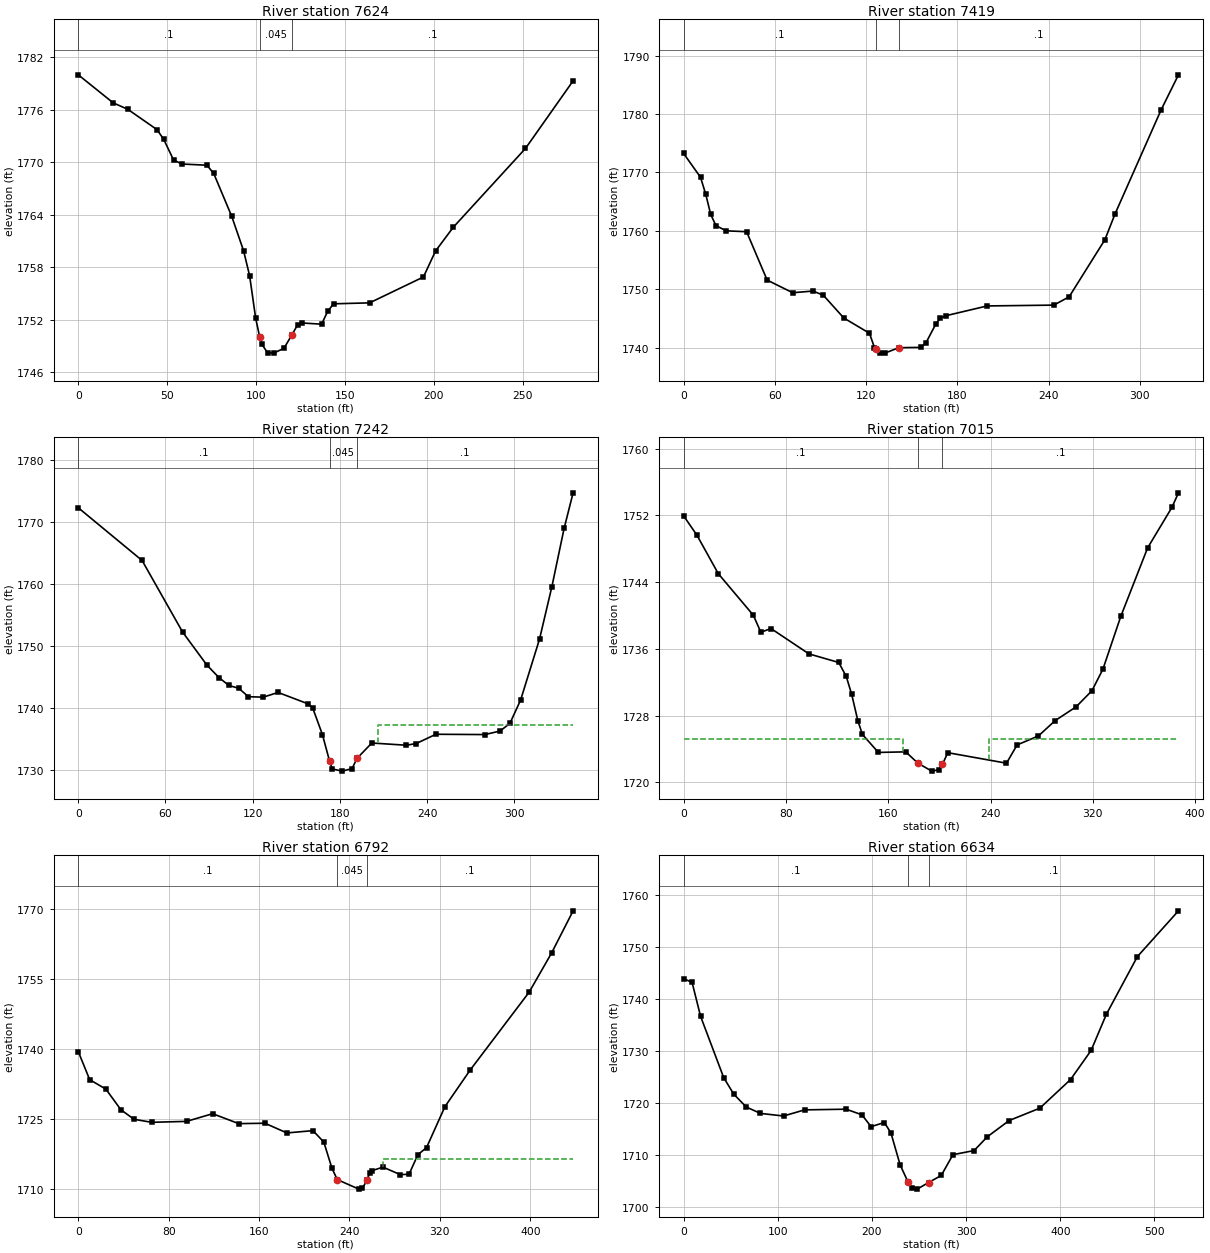
Type RM Length L Ch R = 1 ,7624    ,205.5,205.5,205.5
XS GIS Cut Line= 3
1990399.90017809251617.3083216671990339.99640009 251573.38409907
1990141.42322523251525.963161511
#Sta/Elev= 30
       0    1780    19.6  1776.8    27.9 1776.05    44.3 1773.73    48.1 1772.61
    53.6 1770.26    58.3  1769.8    72.4 1769.66    76.2 1768.72    86.3 1763.83
      93 1759.88    96.4 1757.02    99.8 1752.17   102.1 1749.97   103.2 1749.21
   106.5 1748.21   109.9 1748.17   115.7 1748.72     120 1750.19   123.4 1751.41
   125.8 1751.62   136.9 1751.48   140.3 1752.94   143.6 1753.81   163.9 1753.92
   194.2 1756.88     201 1759.85     211 1762.57   251.6 1771.58   278.4 1779.31
#Mann= 3 ,-1 , 0
       0      .1       0   102.1    .045       0     120      .1       0
Bank Sta=102.1,120
XS Rating Curve= 0 ,0
Exp/Cntr=0.3,0.1

Type RM Length L Ch R = 1 ,7419    ,175.9,177,177.2
XS GIS Cut Line= 2
1990493.32927724251411.7043104511990176.15810365251338.959788698
#Sta/Elev= 30
       0 1773.24    11.1 1769.17    14.5 1766.29    17.8 1762.81    21.2 1760.91
    27.9    1760    41.4 1759.85    54.9 1751.57    71.7  1749.4    85.1 1749.69
    91.9 1748.96   105.3 1745.08   122.2 1742.46   125.5 1739.99   126.4 1739.78
   128.9 1739.08   132.3 1739.06   141.5 1739.99   155.8 1740.04   159.2 1740.76
   165.9 1744.07   168.8 1745.04   172.7 1745.48   199.6 1747.14   243.4 1747.28
   253.5  1748.7     277 1758.47   283.7  1762.9     314 1780.72   325.4 1786.71
#Mann= 3 ,-1 , 0
       0      .1       0   126.4    .045       0   141.5      .1       0
Bank Sta=126.4,141.5
XS Rating Curve= 0 ,0
Exp/Cntr=0.3,0.1

Type RM Length L Ch R = 1 ,7242    ,221.3,227,233
XS GIS Cut Line= 3
1990543.62799627251293.1240563481990470.38527188251231.444733516
1990233.74100373  251168.8962715
#Sta/Elev= 30
       0 1772.34    43.9 1763.83    71.8 1752.27    88.5 1746.95    96.8 1744.93
   103.6 1743.66   110.4  1743.2   117.1 1741.84   127.3 1741.77   137.5 1742.53
   157.9 1740.71   161.3 1740.03     168 1735.73   172.9 1731.46   174.8 1730.18
   181.6 1729.83   188.4 1730.24   191.8 1731.89     202 1734.37   225.7 1734.01
   232.5 1734.28   246.1 1735.78   279.7 1735.73   290.2  1736.3     297 1737.53
   304.4 1741.32   317.4 1751.15   325.9 1759.61   334.3    1769   340.5 1774.75
#Mann= 3 ,-1 , 0
       0      .1       0   172.9    .045       0   191.8      .1       0
#XS Ineff= 2 , 0
                          206.38         1737.32
Permanent Ineff=
       F       F
Bank Sta=172.9,191.8
XS Rating Curve= 0 ,0
Exp/Cntr=0.3,0.1

Type RM Length L Ch R = 1 ,7015    ,209.5,222.7,213.3
XS GIS Cut Line= 2
1990667.81344503251154.1506370481990363.70458997250914.868087934
#Sta/Elev= 30
       0 1751.95    10.4 1749.63    27.1 1745.02    54.5 1740.04    60.4    1738
    68.3 1738.45      98 1735.41   121.3 1734.38   127.2  1732.7   131.4 1730.57
   136.3 1727.37   139.8 1725.76   152.3  1723.6   173.7 1723.67     183 1722.34
     194 1721.36   199.4 1721.52   202.4 1722.17   206.6 1723.57   252.5 1722.31
   260.8  1724.5   277.5 1725.58   290.5 1727.41   306.9 1729.06   319.3 1730.99
   327.9 1733.57   341.9 1739.91   362.9 1748.12   381.9 1752.97     387 1754.71
#Mann= 3 ,-1 , 0
       0      .1       0     183    .045       0   202.4      .1       0
#XS Ineff= 2 , 0
          171.66 1725.16  239.19         1725.24
Permanent Ineff=
       F       F
Bank Sta=183,202.4
XS Rating Curve= 0 ,0
Exp/Cntr=0.3,0.1

Type RM Length L Ch R = 1 ,6792    ,151.3,157.7,158.2
XS GIS Cut Line= 3
  1990731.083011250992.1052784711990420.91569469 250799.16996038
1990348.67309801250792.248513991
#Sta/Elev= 30
       0 1739.43    10.1 1733.43    24.4 1731.42    37.7 1727.01    49.3 1724.97
    64.9 1724.32    95.8 1724.52   118.9 1726.16     142 1724.04   165.2 1724.12
   184.6 1722.05   207.7 1722.54   217.3 1720.09   224.5 1714.49   229.2 1712.08
   248.3 1710.04   251.4 1710.22   255.4 1711.89   257.8 1713.44   260.2    1714
   269.6 1714.75     285 1713.14   292.7 1713.22   300.5 1717.39   308.2 1718.92
   324.5 1727.68   346.8 1735.49     399 1752.14   418.8 1760.48   437.9 1769.52
#Mann= 3 ,-1 , 0
       0      .1       0   229.2    .045       0   255.4      .1       0
#XS Ineff= 1 ,-1
  270.08437.8511 1716.43
Permanent Ineff=
       F
Bank Sta=229.2,255.4
XS Rating Curve= 0 ,0
Exp/Cntr(USF)=0,0
Exp/Cntr=0.3,0.1

Type RM Length L Ch R = 1 ,6634    ,289.9,279.2,268.7
XS GIS Cut Line= 4
1990793.12921018250928.3635981061990656.81803277250777.388463449
1990480.11596446  250626.40050211990391.77427274250610.787951879
#Sta/Elev= 30
       0 1743.89       9 1743.14      18 1736.62    42.5 1724.85    53.2 1721.66
    66.5 1719.18    81.6 1717.95   106.1 1717.45   128.4 1718.63   172.6 1718.76
   189.3 1717.68   199.1  1715.4   213.1  1716.2   220.1 1714.22   229.9 1708.04
   238.5 1704.68   242.8 1703.59     248 1703.38   260.1 1704.65   273.6 1706.01
     286 1710.01   308.5  1710.8   322.4 1713.44   345.7 1716.58   378.3 1718.96
   410.9 1724.47   432.7 1730.06     449 1737.05   481.9 1748.13   525.5 1756.93
#Mann= 3 ,-1 , 0
       0      .1       0   238.5    .045       0   260.1      .1       0
Bank Sta=238.5,260.1
XS Rating Curve= 0 ,0
Exp/Cntr=0.3,0.1

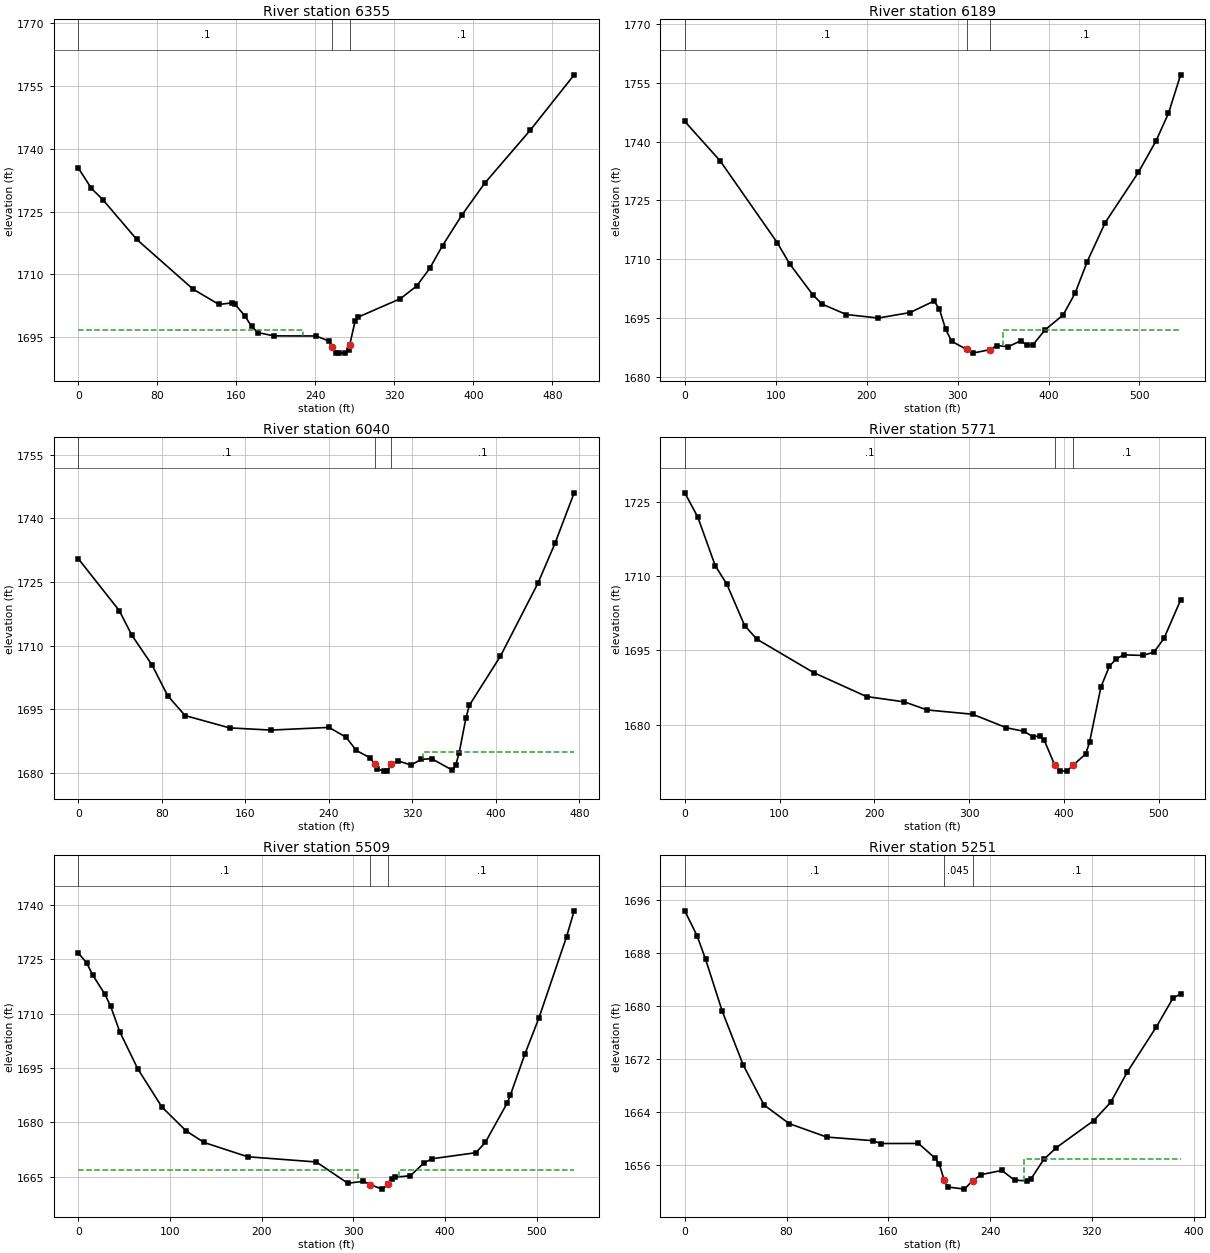
Type RM Length L Ch R = 1 ,6355    ,167.5,166,163.4
XS GIS Cut Line= 3
1990917.20264498250548.3179025161990817.03669918250489.258598341
1990431.36341653250486.319032002
#Sta/Elev= 30
       0 1735.34    13.3 1730.48    24.7 1727.85      59 1718.38   116.3 1706.48
   142.4 1702.86   155.5 1703.24   158.8 1702.87   168.7 1700.11   175.4 1697.63
   181.9 1696.15   198.1 1695.38   240.8 1695.35     254 1694.12   257.2  1692.8
   260.5 1691.39   263.8 1691.27   270.4 1691.27   273.6 1692.12   274.71693.173
   280.2 1698.89   283.5 1699.87   326.1 1704.24   342.5 1707.24   355.7 1711.44
   368.8  1716.9   388.5  1724.2   411.4 1731.73   457.4 1744.32     502 1757.55
#Mann= 3 ,-1 , 0
       0      .1       0   257.2    .045       0   274.7      .1       0
#XS Ineff= 2 , 0
          227.02 1696.77
Permanent Ineff=
       F       F
Bank Sta=257.2,274.7
XS Rating Curve= 0 ,0
Exp/Cntr=0.3,0.1

Type RM Length L Ch R = 1 ,6189    ,147.2,149.3,151.2
XS GIS Cut Line= 3
1990970.69297198250314.2342218071990846.47599754250301.102990159
1990429.80281228250357.153950035
#Sta/Elev= 30
       0 1745.12    38.9 1735.07   101.6 1714.27   115.3 1708.86   141.2 1700.84
   151.2 1698.57   177.7 1695.94   212.7 1695.05   247.7 1696.44     274 1699.36
   279.8 1697.46   286.9 1692.18   293.5 1689.11   310.1 1687.05   316.7 1686.11
   335.2 1686.98   343.2 1688.04   355.7 1687.74   369.7 1689.28   376.3 1688.07
   382.9 1688.21   396.1 1692.02     416  1695.8   429.3  1701.4   442.5 1709.38
   462.4 1719.37   498.8 1732.13   518.1 1740.09   531.9 1747.17   545.3 1756.99
#Mann= 3 ,-1 , 0
       0      .1       0   310.1    .045       0   335.2      .1       0
#XS Ineff= 2 , 0
                             350            1692
Permanent Ineff=
       F       F
Bank Sta=310.1,335.2
XS Rating Curve= 0 ,0
Exp/Cntr=0.3,0.1

Type RM Length L Ch R = 1 ,6040    ,258.7,268.4,277.3
XS GIS Cut Line= 3
1990925.43678358250220.2951586671990852.44827999 250179.94379083
1990460.80265099250180.537193298
#Sta/Elev= 30
       0  1730.5    39.2 1718.28    51.2 1712.49    70.6 1705.45    85.6  1698.2
   102.3 1693.51   144.9 1690.61   184.4 1690.09   240.1 1690.72   256.5 1688.41
   266.3 1685.28   279.5 1683.56     2841682.018     286 1680.97   292.5 1680.41
   295.9 1680.47     3001681.974   305.8 1682.86   318.7 1681.85   328.5 1683.18
   338.4 1683.35   358.4 1680.63   361.5 1681.81   364.8  1684.7   371.3 1692.92
   374.6 1695.94   404.4 1707.53   440.2 1724.68   456.6 1734.11     475 1746.05
#Mann= 3 ,-1 , 0
       0      .1       0     284    .045       0     300      .1       0
#XS Ineff= 2 , 0
                             330            1685
Permanent Ineff=
       F       F
Bank Sta=284,300
XS Rating Curve= 0 ,0
Exp/Cntr(USF)=0,0
Exp/Cntr=0.3,0.1

Type RM Length L Ch R = 1 ,5771    ,266.5,262.8,256.6
XS GIS Cut Line= 2
1990942.05205269250172.8229612121990511.83526325249874.934922183
#Sta/Elev= 30
       0 1726.79    13.7  1721.9    32.2 1712.04    44.2 1708.42    63.2 1699.98
    76.1 1697.25   135.9 1690.51   191.8 1685.67   231.7  1684.6   255.7 1682.97
   303.8  1682.1   339.5 1679.37     358 1678.65   367.4 1677.56   375.4 1677.74
   379.4 1676.84   390.5 1671.81   395.7 1670.62   403.3 1670.66   409.9 1671.82
   423.3 1674.14   427.3 1676.58   439.2  1687.6   448.1 1691.79   455.2 1693.25
   463.2 1694.09   483.1 1693.97   495.1 1694.62   505.8 1697.44   523.3 1705.16
#Mann= 3 ,-1 , 0
       0      .1       0   390.5    .045       0   409.9      .1       0
Bank Sta=390.5,409.9
XS Rating Curve= 0 ,0
Exp/Cntr(USF)=0,0
Exp/Cntr=0.3,0.1

Type RM Length L Ch R = 1 ,5509    ,261,257.2,252.1
XS GIS Cut Line= 3
1991039.41753148 249761.249066641990902.84723321 249767.58014007
 1990513.9384368249658.143013641
#Sta/Elev= 30
       0 1726.67       9 1723.99    15.6 1720.64    28.7 1715.42    35.3 1711.99
    45.1 1705.02    64.8 1694.76    91.1 1684.24   117.5 1677.66   137.1 1674.45
   184.8 1670.51   259.5 1669.08   293.9 1663.21   310.9 1663.75   318.5 1662.82
   331.4 1661.59   338.2 1662.91   341.6 1664.41     345 1664.88   362.1 1665.28
     377 1668.84   385.9 1669.97   433.6 1671.64   443.9  1674.5   467.5 1685.26
   471.1 1687.49   487.1 1698.91   502.1 1708.66   532.5 1731.24   540.7 1738.32
#Mann= 3 ,-1 , 0
       0      .1       0   318.5    .045       0   338.2      .1       0
#XS Ineff= 2 , 0
             305    1667     350            1667
Permanent Ineff=
       F       F
Bank Sta=318.5,338.2
XS Rating Curve= 0 ,0
Exp/Cntr(USF)=0,0
Exp/Cntr=0.3,0.1

Type RM Length L Ch R = 1 ,5251    ,322,331.2,339.1
XS GIS Cut Line= 2
 1990977.9156753249465.4974935621990588.10243984249470.019688869
#Sta/Elev= 30
       0  1694.3     9.8 1690.48    16.4 1686.98    29.5 1679.16    45.9 1671.13
    62.3  1665.1      82  1662.3   111.6 1660.27   147.6 1659.73   154.2  1659.3
   183.7 1659.31   196.9 1657.08   200.1 1656.17   203.8 1653.88   206.7 1652.77
   219.8 1652.44   226.3 1653.71     233 1654.62   249.2 1655.25   259.2  1653.8
     269 1653.67   272.3 1654.02   282.2  1656.9     292 1658.67   321.5 1662.75
   334.7 1665.47   347.8 1670.03   370.8 1676.87   383.9  1681.2   389.8 1681.78
#Mann= 3 ,-1 , 0
       0      .1       0   203.8    .045       0   226.3      .1       0
#XS Ineff= 2 , 0
                             267            1657
Permanent Ineff=
       F       F
Bank Sta=203.8,226.3
XS Rating Curve= 0 ,0
Exp/Cntr(USF)=0,0
Exp/Cntr=0.3,0.1

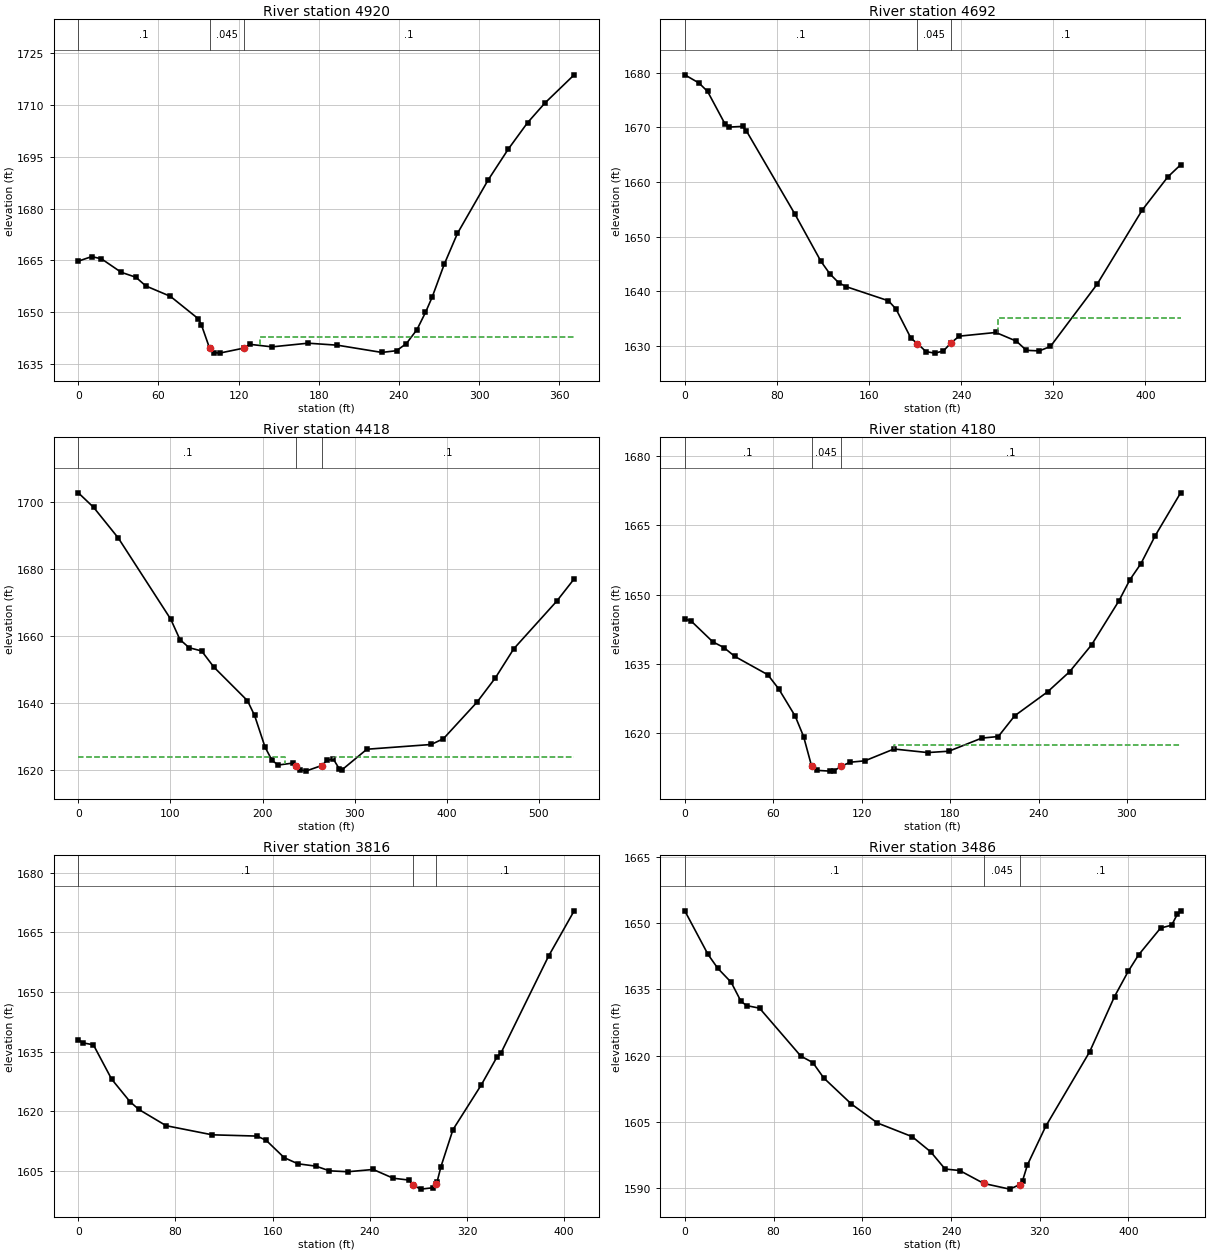
Type RM Length L Ch R = 1 ,4920    ,215.8,227.8,237.7
XS GIS Cut Line= 3
1990839.16874494249238.767653835 1990603.1132431249118.603654028
1990496.83486105 249119.67177847
#Sta/Elev= 30
       0 1664.81      10 1666.12    17.3 1665.48    32.1 1661.59    43.1 1660.16
    50.5 1657.65    68.9 1654.65    89.7  1648.2    92.1 1646.46    98.3 1639.62
   101.6  1638.4   105.7 1638.24   123.8 1639.68   128.7 1640.77     145 1640.05
     172 1641.11     194 1640.53   227.2 1638.44   238.2 1638.94   245.6    1641
   253.5 1645.02   259.9    1650   264.9 1654.42   273.9 1663.87   283.8 1672.81
   306.7 1688.19   321.8 1697.13   336.3  1704.8   349.4 1710.52   371.2 1718.63
#Mann= 3 ,-1 , 0
       0      .1       0    98.3    .045       0   123.8      .1       0
#XS Ineff= 1 ,-1
  136.08371.1641    1643
Permanent Ineff=
       F
Bank Sta=98.3,123.8
XS Rating Curve= 0 ,0
Exp/Cntr(USF)=0,0
Exp/Cntr=0.3,0.1

Type RM Length L Ch R = 1 ,4692    ,292.8,274.3,246.7
XS GIS Cut Line= 3
1990932.16620815249173.730987274 1990763.6280413248883.116975034
1990668.92449815248887.251325747
#Sta/Elev= 30
       0 1679.66    12.3 1678.16    19.8 1676.61      35 1670.62    38.8 1670.08
    50.2  1670.2    53.5 1669.38    95.7  1654.1   118.3 1645.44     126 1643.16
   133.6 1641.55   139.9 1640.83   176.9 1638.22   183.5  1636.7   196.5 1631.33
   202.11630.375   209.5  1628.9   217.1 1628.62   224.6 1629.01   230.91630.428
   238.3 1631.73   270.2 1632.41   288.1 1630.81   296.7 1629.13   307.9 1629.03
   317.6 1629.84   358.1 1641.24   397.3 1654.85   419.5 1660.92   430.7 1663.16
#Mann= 3 ,-1 , 0
       0      .1       0   202.1    .045       0   230.9      .1       0
#XS Ineff= 2 , 0
                          272.15            1635
Permanent Ineff=
       F       F
Bank Sta=202.1,230.9
XS Rating Curve= 0 ,0
Exp/Cntr=0.3,0.1

Type RM Length L Ch R = 1 ,4418    ,243,238.5,233
XS GIS Cut Line= 3
1991151.64323725 248770.489239261991018.41704838248743.294075707
1990621.21163255248806.919478905
#Sta/Elev= 30
       0 1702.89    16.6 1698.54    43.4 1689.36   100.3 1665.08   110.3 1658.98
   120.3 1656.54   133.8 1655.58   147.1 1650.75   183.6 1640.69   191.3 1636.29
   202.7 1626.78   210.2 1622.86   216.9 1621.44   233.5 1622.05   236.8 1621.08
   240.1 1620.05   246.8 1619.62   264.1 1621.28     270 1622.84   276.7 1623.27
   283.3 1620.28   286.6  1620.1   313.2 1626.17     383 1627.59   396.3 1629.32
   432.8 1640.27   452.8 1647.57   472.7 1656.24   519.2 1670.45   538.2 1677.14
#Mann= 3 ,-1 , 0
       0      .1       0   236.8    .045       0   264.1      .1       0
#XS Ineff= 2 , 0
          224.48 1623.97   276.7         1623.99
Permanent Ineff=
       F       F
Bank Sta=236.8,264.1
XS Rating Curve= 0 ,0
Exp/Cntr=0.3,0.1

Type RM Length L Ch R = 1 ,4180    ,353.9,363.8,368
XS GIS Cut Line= 2
1990952.02358781248491.8238842961990655.61905495248650.974426264
#Sta/Elev= 30
       0 1644.67     4.1 1644.31      19 1639.73    26.5 1638.49    33.9 1636.57
    56.3 1632.59    63.7 1629.53    74.9  1623.6    80.6 1619.17      86 1612.78
    89.8 1611.82    98.7 1611.66   101.1  1611.7   105.9 1612.67   112.1 1613.59
   122.2  1613.9   141.9 1616.46   164.8 1615.69   179.1 1615.98   201.5 1618.83
   212.7 1619.17   223.8 1623.67   246.2 1628.89   261.1 1633.25     276 1639.08
   294.6 1648.66     302 1653.22   309.5 1656.72   319.1 1662.74   336.4 1672.08
#Mann= 3 ,-1 , 0
       0      .1       0      86    .045       0   105.9      .1       0
#XS Ineff= 2 , 0
                          142.17         1617.39
Permanent Ineff=
       F       F
Bank Sta=86,105.9
XS Rating Curve= 0 ,0
Exp/Cntr(USF)=0,0
Exp/Cntr=0.3,0.1

Type RM Length L Ch R = 1 ,3816    ,312.6,330.1,340
XS GIS Cut Line= 3
1990965.84140791248347.1252890761990762.27948146248235.610474988
1990586.15832945248239.129944551
#Sta/Elev= 30
       0 1637.95     3.9 1637.18    12.4  1636.7    27.4 1628.08    42.5 1622.42
    49.8 1620.46    72.3 1616.37   110.2 1614.08   147.1 1613.76   154.6 1612.72
   169.5 1608.34   180.8  1606.8   195.7  1606.2   206.8 1605.03   221.9  1604.8
   242.8 1605.37   259.3 1603.17   272.4  1602.7   275.7 1601.35   282.2 1600.43
   292.1 1600.78   294.21601.622   295.3 1602.11   298.6 1606.07   308.5 1615.38
   331.8 1626.61   344.6 1633.56   347.9 1634.56   387.2 1658.97   408.3 1670.37
#Mann= 3 ,-1 , 0
       0      .1       0   275.7    .045       0   294.2      .1       0
Bank Sta=275.7,294.2
XS Rating Curve= 0 ,0
Exp/Cntr=0.3,0.1

Type RM Length L Ch R = 1 ,3486    ,317.2,307.3,299.4
XS GIS Cut Line= 2
1991099.88841254248211.0534307861990805.22216634247874.873431663
#Sta/Elev= 30
       0 1652.83    20.9 1642.96    29.7 1639.81    41.8 1636.63    50.7 1632.29
    55.8 1631.34    67.4 1630.76   104.6  1619.9   115.4 1618.43   125.3 1614.93
   150.2 1609.03   173.7 1604.73     205 1601.63   221.7 1598.19   234.7 1594.29
   247.8 1593.96   269.6 1591.02   292.9 1589.74   302.2 1590.78   304.5 1591.64
   308.9 1595.24   325.4 1603.99     365 1620.88   387.4  1633.4   399.8 1639.13
   409.1 1642.84   428.9 1648.92   438.9 1649.58     444 1652.04     447  1652.8
#Mann= 3 ,-1 , 0
       0      .1       0   269.6    .045       0   302.2      .1       0
Bank Sta=269.6,302.2
XS Rating Curve= 0 ,0
Exp/Cntr(USF)=0,0
Exp/Cntr=0.3,0.1

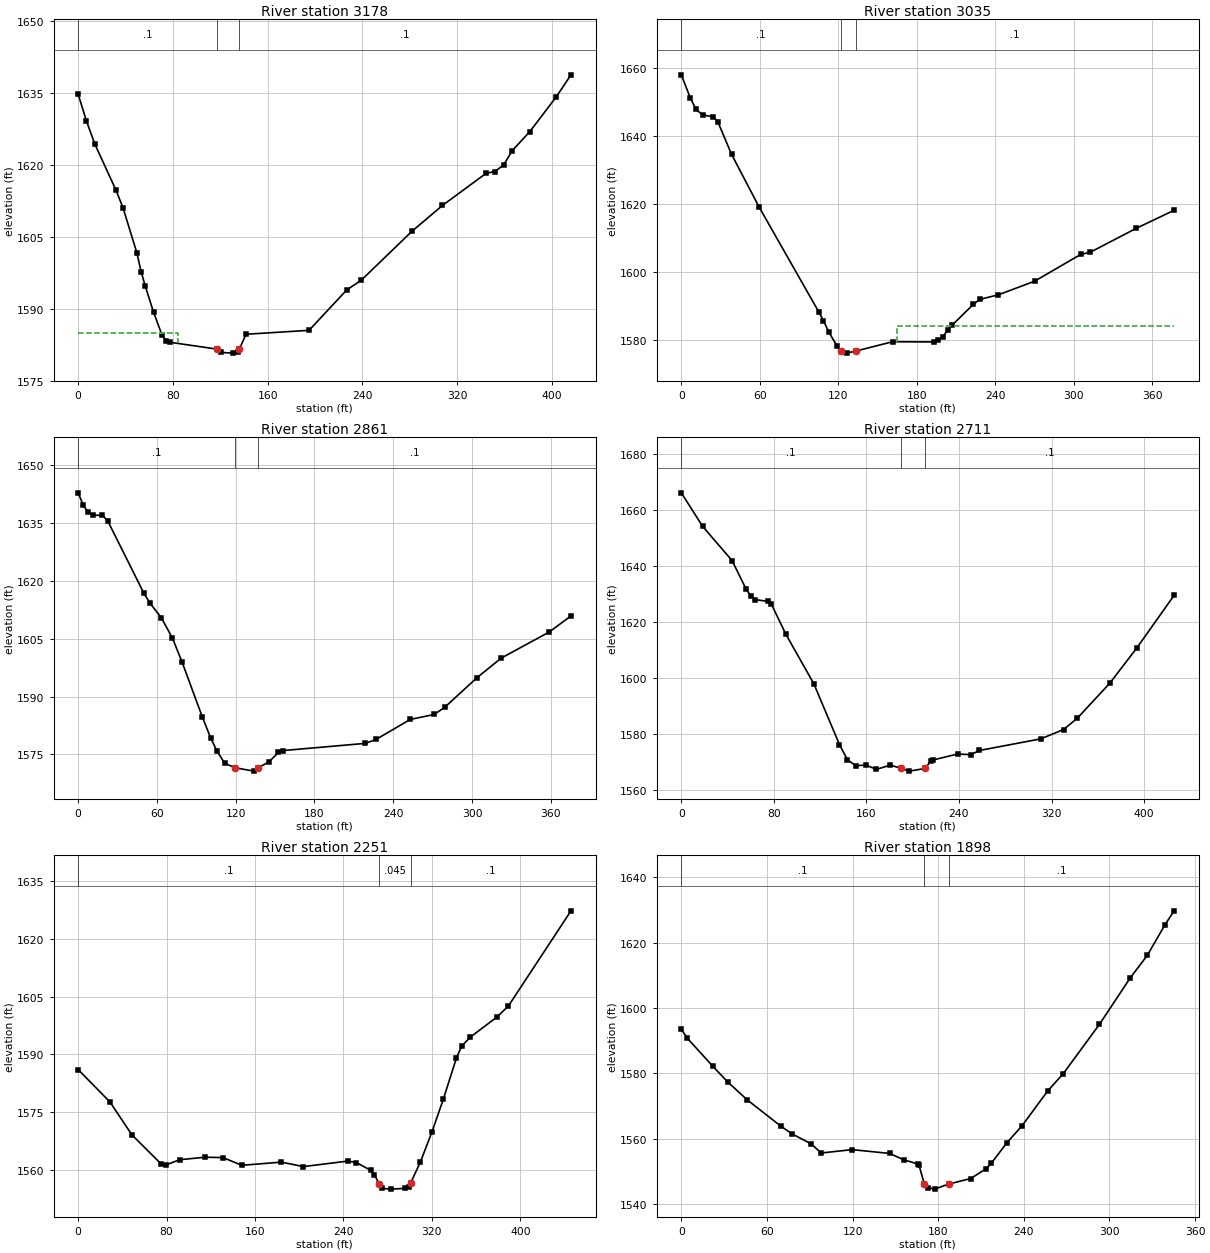
Type RM Length L Ch R = 1 ,3178    ,152.9,143.6,133.1
XS GIS Cut Line= 3
1991181.28792807247788.589945205 1990960.1565523247698.333363355
1990802.72198943247779.627169566
#Sta/Elev= 30
       0 1634.79       7 1629.21    14.1 1624.38    31.8 1614.84    37.8 1611.13
    49.6 1601.66    53.1 1597.78    56.7 1594.69    63.7 1589.25    70.8 1584.52
    74.4 1583.34    77.9 1583.01   116.9 1581.61   120.4 1580.91   130.6 1580.76
   134.6 1580.98     136 1581.57   141.7  1584.7   194.9 1585.52   226.7 1593.95
     239 1595.99   281.6 1606.16   307.5 1611.59   344.4 1618.31   351.8 1618.67
   359.2 1620.06   366.5 1623.06   381.3 1627.02   403.5 1634.23     416 1638.86
#Mann= 3 ,-1 , 0
       0      .1       0   116.9    .045       0     136      .1       0
#XS Ineff= 2 , 0
              84    1585
Permanent Ineff=
       F       F
Bank Sta=116.9,136
XS Rating Curve= 0 ,0
Exp/Cntr=0.3,0.1

Type RM Length L Ch R = 1 ,3035    ,182.4,173.9,163.2
XS GIS Cut Line= 2
1991181.06877062247560.4098146861990829.50627062247696.043495238
#Sta/Elev= 30
       0 1658.02     6.8  1651.3    11.2 1647.85    16.3 1646.24    24.3 1645.67
    27.9 1644.22    38.4 1634.64    59.5 1619.11   105.2  1588.2   108.7 1585.71
   112.7 1582.37   119.3 1578.13     122 1576.81   122.9 1576.42   126.3 1576.15
   133.61576.776   161.5  1579.5   193.1 1579.44   196.5 1579.87   200.2 1581.04
   203.7 1582.98   207.2 1584.43   223.4 1590.55   228.3 1591.97   242.4  1593.3
   270.1 1597.31   305.4 1605.19   312.7 1605.83   347.9 1612.88   376.8 1618.17
#Mann= 3 ,-1 , 0
       0      .1       0     122    .045       0   133.6      .1       0
#XS Ineff= 2 , 0
                             165            1584
Permanent Ineff=
       F       F
Bank Sta=122,133.6
XS Rating Curve= 0 ,0
Exp/Cntr(USF)=0,0
Exp/Cntr=0.3,0.1

Type RM Length L Ch R = 1 ,2861    ,145.3,149.8,154.1
XS GIS Cut Line= 3
1991035.66946509247352.0764813571990924.99238175247559.324745238
1990812.14515951247642.875092462
#Sta/Elev= 30
       0 1642.87     3.8  1639.7     7.5 1637.85    11.2 1637.09    18.5    1637
    22.4 1635.65      50 1616.85    54.8 1614.19    63.3  1610.5    71.8 1605.18
    79.1 1599.02    94.7 1584.61   100.9 1579.32   105.7  1575.9   111.6 1572.74
   119.1 1571.58   133.9 1570.68   137.31571.614   145.1 1573.01   152.5 1575.52
   156.3 1576.02   218.8 1577.88     227 1578.91     253  1584.1   271.2 1585.37
   279.3 1587.26   303.8 1594.92   322.3 1600.01   358.6 1606.72   375.4 1610.93
#Mann= 3 ,-1 , 0
       0      .1       0   119.1    .045       0   137.3      .1       0
Bank Sta=119.1,137.3
XS Rating Curve= 0 ,0
Exp/Cntr(USF)=0,0
Exp/Cntr=0.3,0.1

Type RM Length L Ch R = 1 ,2711    ,461.8,459.8,449.2
XS GIS Cut Line= 2
 1990984.3011005247253.7951281971990686.37887367247558.229316265
#Sta/Elev= 30
       0    1666    18.4 1654.03    43.9 1641.78      56 1631.62    60.1 1629.08
    64.1 1627.85    74.8 1627.24    77.9 1626.19    90.3 1615.55   114.6 1597.76
   136.7 1576.11   143.6 1570.67   150.6 1568.61   159.9 1568.72   168.6 1567.24
   180.8 1568.76     190 1567.58   197.2 1566.61   210.9 1567.58   215.5  1570.2
   217.9 1570.62   238.8 1572.72   250.4  1572.5   257.7 1573.98   310.7 1578.13
   330.4 1581.47   342.2 1585.46   370.3 1597.97   393.8 1610.62     426  1629.4
#Mann= 3 ,-1 , 0
       0      .1       0     190    .045       0   210.9      .1       0
Bank Sta=190,210.9
XS Rating Curve= 0 ,0
Exp/Cntr(USF)=0,0
Exp/Cntr=0.3,0.1

Type RM Length L Ch R = 1 ,2251    ,321.1,353.4,384
XS GIS Cut Line= 3
 1990760.4524328    247184.605541990552.88366821247207.397404347
1990477.18211877  247432.0600672
#Sta/Elev= 30
       0    1586    28.8 1577.57    48.6 1569.03      75 1561.47    79.6 1561.21
    91.8 1562.55   114.6  1563.2   131.1 1563.11     148  1561.1   183.9 1561.93
   203.7 1560.76   243.8 1562.19   251.7 1561.83   264.6 1559.79     268 1558.67
   272.4 1556.24     275 1555.09   282.8  1554.9   295.7 1555.09   299.2 1555.57
   300.9 1556.53   309.6 1561.94     320  1569.7   330.4 1578.29   342.3 1589.08
     347  1592.1   354.6 1594.41   378.6 1599.62   389.2 1602.52   445.9 1627.33
#Mann= 3 ,-1 , 0
       0      .1       0   272.4    .045       0   300.9      .1       0
Bank Sta=272.4,300.9
XS Rating Curve= 0 ,0
Exp/Cntr(USF)=0,0
Exp/Cntr=0.3,0.1

Type RM Length L Ch R = 1 ,1898    ,237.5,236.4,235.3
XS GIS Cut Line= 3
1990747.42851032247069.0182279521990671.72696088247086.112126213
1990428.34240945246974.594789942
#Sta/Elev= 30
       0 1593.45     4.3 1590.65      22 1582.15    32.4 1577.36    46.2 1571.83
    69.8 1563.76    77.6 1561.42    90.9 1558.38    98.1 1555.57   119.7  1556.6
   145.9 1555.44   155.8  1553.5   165.7 1552.21   166.6 1551.79   170.3 1545.98
   173.1    1545   177.5 1544.51   187.3 1546.06   202.8 1547.76   213.6 1550.78
   217.2 1552.42     228 1558.64   238.8 1563.94   256.9 1574.66   267.7  1579.9
     293 1594.97   314.6 1609.19   326.6 1616.13   338.9 1625.44   345.3  1629.7
#Mann= 3 ,-1 , 0
       0      .1       0   170.3    .045       0   187.3      .1       0
Bank Sta=170.3,187.3
XS Rating Curve= 0 ,0
Exp/Cntr(USF)=0,0
Exp/Cntr=0.3,0.1

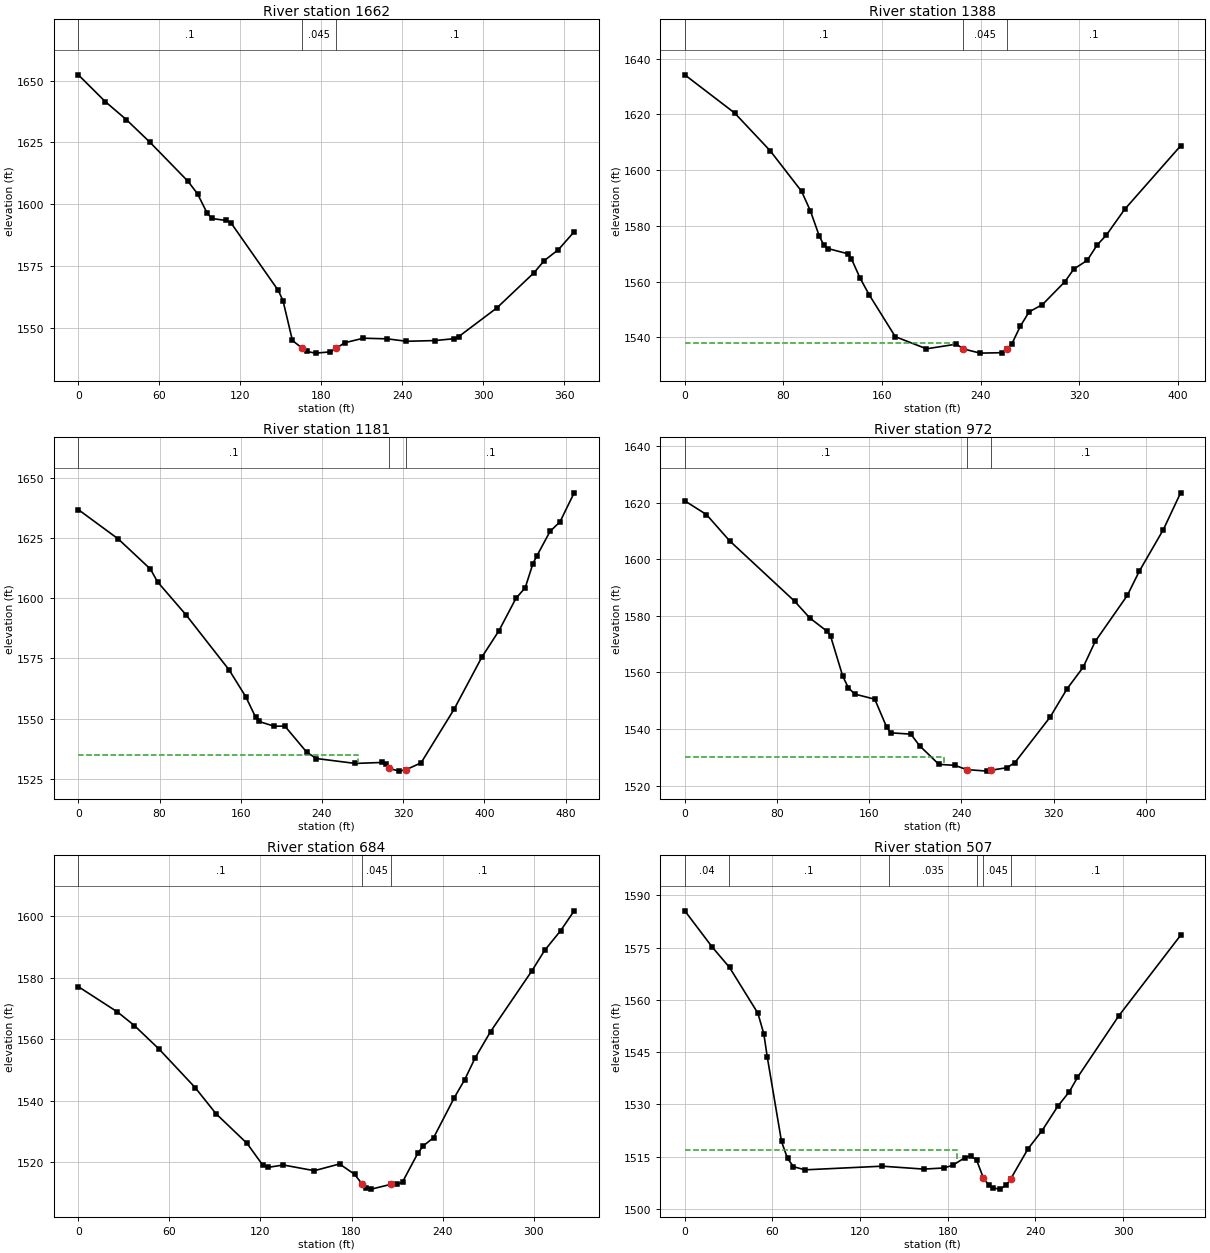
Type RM Length L Ch R = 1 ,1662    ,269.9,273.9,275.8
XS GIS Cut Line= 2
 1990850.2284728246896.7460193791990507.77276944246763.922515526
#Sta/Elev= 30
       0 1652.42      20 1641.54    35.5  1634.3    53.1 1625.07    81.2  1609.3
    88.3 1604.21    95.3 1596.51    98.8 1594.21   109.4  1593.4   112.9 1592.58
   148.1 1565.05   151.6 1560.95   158.6 1544.77   165.7 1541.71   169.2 1540.33
   175.7 1539.65   186.8 1540.16   190.9 1541.55   197.3 1543.85   211.2  1545.7
     229 1545.43   243.1 1544.45   264.2 1544.74   278.3  1545.5   281.8 1546.34
   310.1    1558   337.6 1572.25   345.1 1577.11   355.7 1581.62   367.3 1588.81
#Mann= 3 ,-1 , 0
       0      .1       0   165.7    .045       0   190.9      .1       0
Bank Sta=165.7,190.9
XS Rating Curve= 0 ,0
Exp/Cntr=0.3,0.1

Type RM Length L Ch R = 1 ,1388    ,203,206.5,208
XS GIS Cut Line= 2
1990935.73317243246674.5055619891990571.39382845246503.980469939
#Sta/Elev= 30
       0 1634.23    40.4 1620.54    69.3 1606.95    94.7 1592.44   101.9  1585.4
   109.2 1576.23   112.8 1573.17   116.4 1571.82   132.3 1569.98   135.2 1568.18
   142.1 1561.34   149.5 1555.32   170.8  1540.2   196.1 1535.85   220.3 1537.52
     226 1535.81   239.6  1534.3   257.7 1534.46   261.3 1535.63   265.5 1537.75
   272.2 1543.94   279.4 1549.12   290.2 1551.74   308.4 1559.95   315.7 1564.51
   326.5 1567.61   334.6 1573.15     342 1576.65   356.8 1585.88   402.3 1608.74
#Mann= 3 ,-1 , 0
       0      .1       0     226    .045       0   261.3      .1       0
#XS Ineff= 2 , 0
           217.9 1538.06
Permanent Ineff=
       F       F
Bank Sta=226,261.3
XS Rating Curve= 0 ,0
Exp/Cntr=0.3,0.1

Type RM Length L Ch R = 1 ,1181    ,200.3,209.5,218.9
XS GIS Cut Line= 3
1991007.81591566246624.2435765241990948.48531367  246473.1737743
1990667.37885267246307.925634661
#Sta/Elev= 30
       0  1636.7    39.3 1624.53      71 1612.03    78.1 1606.69   106.3 1592.93
   148.6 1570.16     165 1559.03   174.6 1550.61   177.6 1548.88   192.9 1546.85
   203.4 1546.92   224.9 1536.11   234.5 1533.46   272.8 1531.42   299.2 1531.83
   303.2 1531.17   306.4 1529.34     316 1528.23   323.2 1528.89   337.6 1531.67
   370.1 1553.88   397.5 1575.53   414.3 1586.45     431 1599.86   440.2  1604.3
   447.8 1614.33   451.6 1617.45   464.6 1627.63   474.5 1631.67   488.4 1643.66
#Mann= 3 ,-1 , 0
       0      .1       0   306.4    .045       0   323.2      .1       0
#XS Ineff= 2 , 0
             275    1535
Permanent Ineff=
       F       F
Bank Sta=306.4,323.2
XS Rating Curve= 0 ,0
Exp/Cntr=0.3,0.1

Type RM Length L Ch R = 1 ,972     ,285.6,288,287.8
XS GIS Cut Line= 2
 1991081.8683762246572.5953121911990939.75932805246166.640584258
#Sta/Elev= 30
       0 1620.62    18.8 1615.76    38.8 1606.52    95.3 1585.13   108.4 1579.23
   123.1 1574.62   126.5 1572.76     137 1558.67   141.8 1554.62   147.4 1552.34
   164.8 1550.53   175.2 1540.55   178.7 1538.64   196.1 1538.18   203.6 1534.12
   220.4  1527.5   234.3 1527.15   244.5 1525.66   262.1 1525.11   265.6 1525.42
   279.5 1526.33   286.4 1528.15   316.9  1544.2   331.6  1554.2   345.5 1561.78
     356 1570.93   383.9 1587.22   394.2 1595.72   415.1 1610.44   430.1 1623.45
#Mann= 3 ,-1 , 0
       0      .1       0   244.5    .045       0   265.6      .1       0
#XS Ineff= 2 , 0
             225    1530
Permanent Ineff=
       F       F
Bank Sta=244.5,265.6
XS Rating Curve= 0 ,0
Exp/Cntr=0.3,0.1

Type RM Length L Ch R = 1 ,684     ,181.8,176.8,171.9
XS GIS Cut Line= 2
1991320.37713499246438.5680421851991229.77722667246124.641581663
#Sta/Elev= 30
       0 1577.15    25.8  1568.9    36.9 1564.49    53.1 1556.86      77 1544.26
    90.7 1535.78   111.2 1526.09   121.4  1519.1   124.8 1518.28   135.1 1519.07
   155.5 1517.21   172.1 1519.41     182 1516.05   187.21512.743   189.7 1511.52
   193.1 1511.21   205.7 1512.75   210.2 1512.74   213.6 1513.53   223.8    1523
   227.3 1525.31   234.1 1527.97   247.7 1540.97   254.6 1546.88   261.4 1553.88
   271.6  1562.5     299  1582.4   307.2 1588.93   317.8 1595.39   326.7 1601.84
#Mann= 3 ,-1 , 0
       0      .1       0   187.2    .045       0   205.7      .1       0
Bank Sta=187.2,205.7
XS Rating Curve= 0 ,0
Exp/Cntr(USF)=0,0
Exp/Cntr=0.3,0.1

Type RM Length L Ch R = 1 ,507     ,201,186.7,174.6
XS GIS Cut Line= 2
1991544.37707373246336.2179211621991345.31793479246061.310702794
#Sta/Elev= 30
       0 1585.58    18.8 1575.16    30.6 1569.33      50  1556.2    54.1 1550.25
    56.4 1543.74    66.2 1519.34    70.3  1514.5    74.4  1512.1    82.3  1511.2
   135.1 1512.25   163.5 1511.41   177.1 1511.73   183.3 1512.48   191.8 1514.71
   195.9 1515.19   199.7 1514.03   204.4 1508.84     208 1506.84   210.7    1506
   215.8 1505.66   220.2 1506.87   223.2 1508.68     235 1517.28   244.5 1522.42
   255.4 1529.51   263.2 1533.62   268.8 1537.74   297.1 1555.44   339.4 1578.56
#Mann= 6 ,-1 , 0
       0     .04       0      30      .1       0     140    .035       0
     200      .1       0   204.4    .045       0   223.2      .1       0
#XS Ineff= 2 , 0
          186.59  1516.8
Permanent Ineff=
       F       F
Bank Sta=204.4,223.2
XS Rating Curve= 0 ,0
Exp/Cntr(USF)=0,0
Exp/Cntr=0.3,0.1