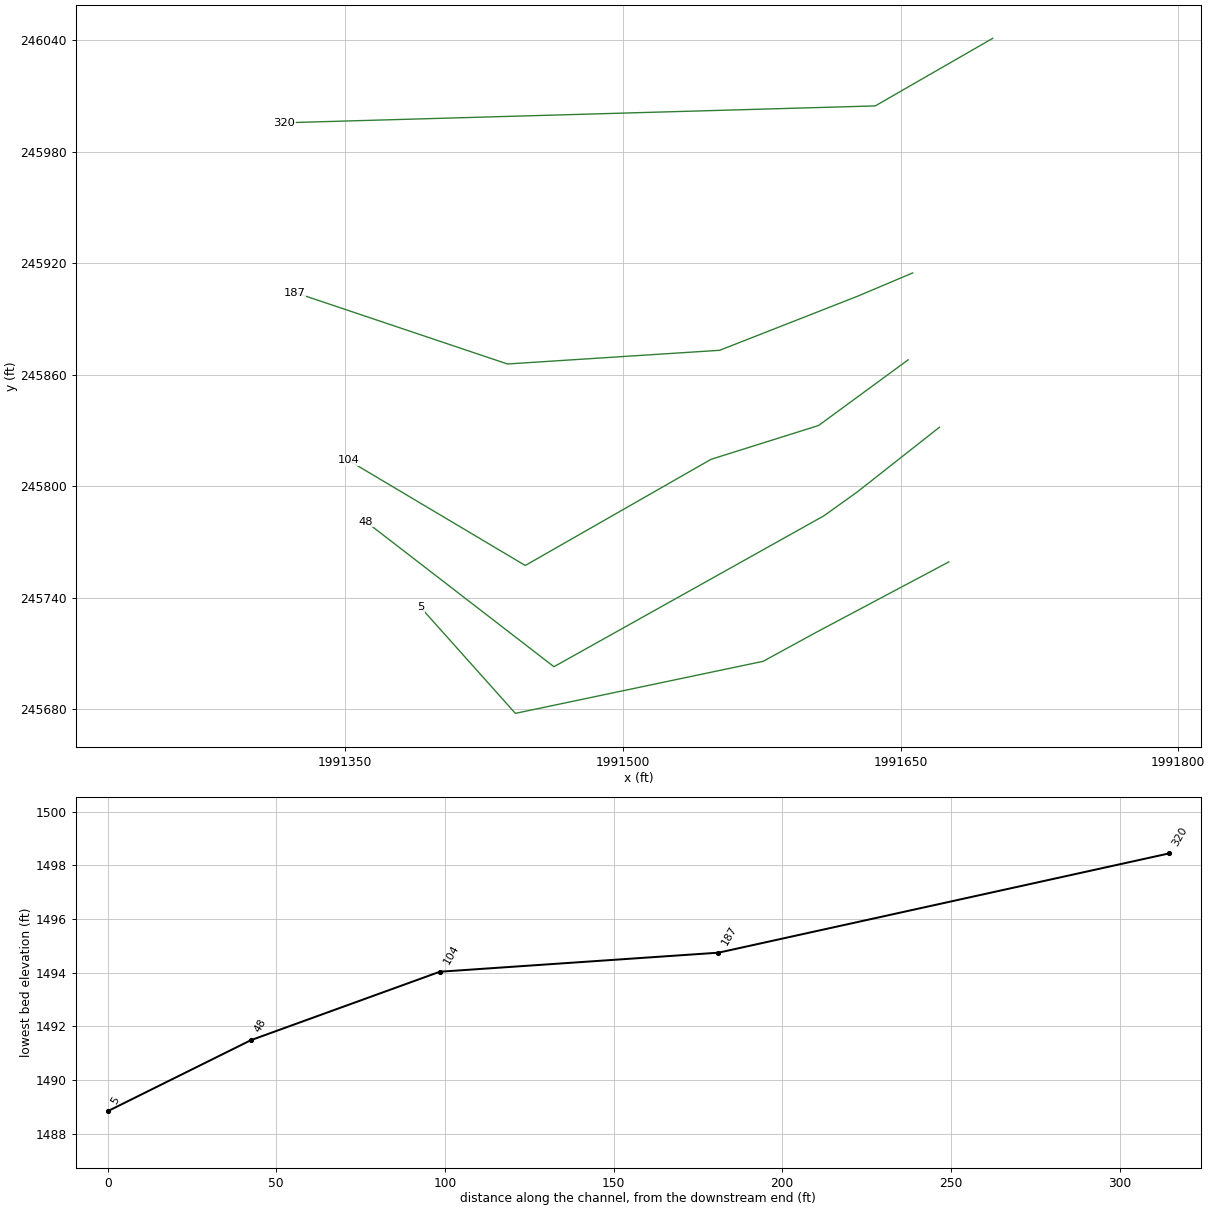
HEC-RAS study RFKMADAMCK.prj: RFKMADAMCK

--- RFKMADAMCK.g01 (geometry) --- (continued)

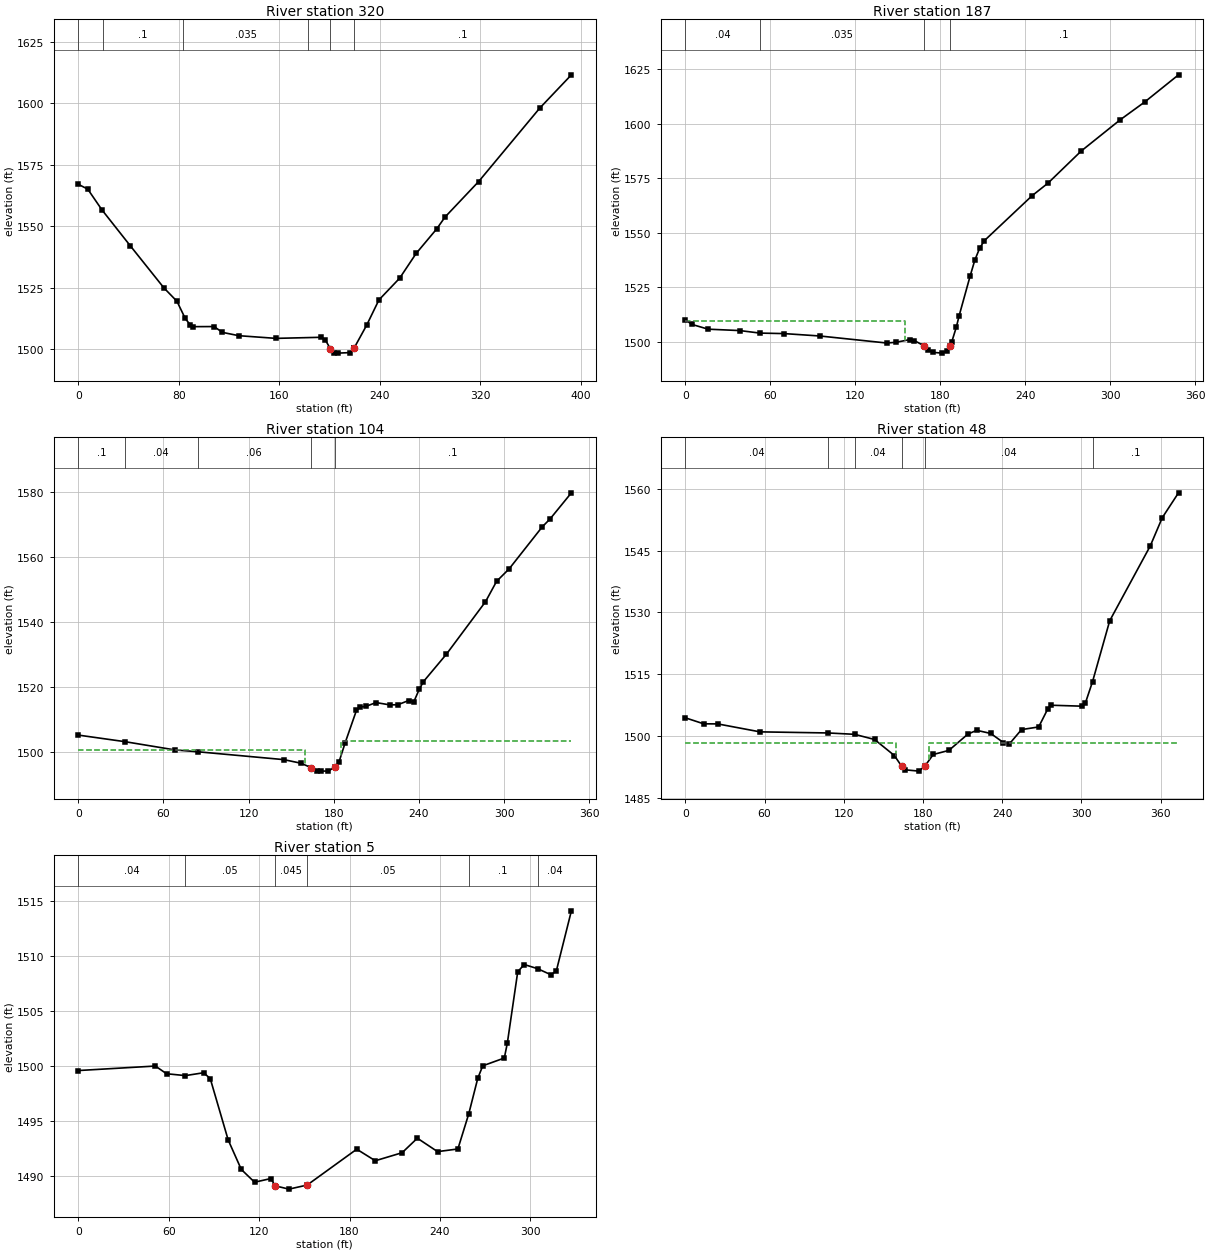
Type RM Length L Ch R = 1 ,320     ,133.2,133.6,134.3
XS GIS Cut Line= 3
1991699.73877305246041.0073437351991636.28889984246004.649418041
1991316.91969147245995.570360278
#Sta/Elev= 30
       0  1567.1     7.6 1565.11    18.9 1556.68    41.6 1541.99    68.2 1524.98
    78.6 1519.52    85.2 1512.53      89 1510.06    91.7  1509.2   108.2 1509.24
   114.7 1506.89   127.8 1505.53   157.4 1504.44   193.5 1504.88   196.8 1503.74
   200.7 1500.24   203.3 1498.67   206.6 1498.44   216.5 1498.65   219.7 1500.53
   219.7 1500.56   229.6 1509.77   239.4 1520.08   255.9 1528.91     269 1538.96
   285.4 1548.95     292 1553.75   318.8 1568.21   367.4 1598.04   392.6 1611.58
#Mann= 6 ,-1 , 0
       0     .04       0      20      .1       0   83.13    .035       0
  183.13      .1       0   200.7    .045       0   219.7      .1       0
Bank Sta=200.7,219.7
XS Rating Curve= 0 ,0
Exp/Cntr(USF)=0,0
Exp/Cntr=0.3,0.1

Type RM Length L Ch R = 1 ,187     ,76.1,82.6,88.4
XS GIS Cut Line= 5
1991656.52716371 245914.792089111991626.81638939245902.278098775
1991552.24515044 245873.15297428 1991437.6177535245865.793240485
 1991322.7943759245904.245720424
#Sta/Elev= 30
       0 1510.15     4.4 1507.97    16.1 1505.73    38.5 1505.09    52.6 1503.94
    69.9  1503.7    94.9 1502.61   142.1 1499.39   148.6 1499.69   158.5 1500.94
   161.8 1500.49   168.3  1498.2   171.7 1496.05   174.9 1495.09   181.5 1494.74
   184.8 1495.84   186.8 1498.13   188.1 1499.78   191.4  1506.7   193.4 1511.98
   201.2 1530.27   204.5 1537.52   207.8 1542.78   211.1  1546.3   244.9 1566.99
   256.1 1572.74   279.6  1587.5   307.1 1601.81   324.4 1609.98   348.3 1622.46
#Mann= 4 ,-1 , 0
       0     .04       0    52.6    .035       0   168.3    .045       0
   186.8      .1       0
#XS Ineff= 2 , 0
          155.06 1509.61
Permanent Ineff=
       F       F
Bank Sta=168.3,186.8
XS Rating Curve= 0 ,0
Exp/Cntr(USF)=0,0
Exp/Cntr=0.5,0.3

Type RM Length L Ch R = 1 ,104     ,56.1,56,55.9
XS GIS Cut Line= 5
  1991654.096539245868.044044523 1991605.6460893 245832.68138276
 1991547.6345711245814.5232672341991447.23087348245757.378609548
1991351.63373585245813.989205013
#Sta/Elev= 30
       0 1505.15    32.9 1503.12      68 1500.58    84.1 1500.01   144.8 1497.58
   156.8 1496.48     1641495.127   168.5 1494.13   171.3 1494.03   176.1 1494.06
   180.9 1495.27   183.6 1496.71   188.1 1502.85     196 1512.77   198.7 1513.82
   202.5 1513.98   209.8 1515.18   219.4 1514.47   225.1  1514.5   232.7  1515.8
   236.3 1515.31   240.3 1519.34   243.2 1521.65   259.4 1530.12   286.9 1546.29
   294.7 1552.57   303.6 1556.45   326.9  1569.4   332.4 1571.83   347.4 1579.88
#Mann= 5 ,-1 , 0
       0      .1       0    32.9     .04       0    84.1     .06       0
     164    .045       0   180.9      .1       0
#XS Ineff= 2 , 0
             160  1500.4     185          1503.3
Permanent Ineff=
       F       F
Bank Sta=164,180.9
XS Rating Curve= 0 ,0
Exp/Cntr(USF)=0,0
Exp/Cntr=0.5,0.3

Type RM Length L Ch R = 1 ,48      ,42.5,42.5,42.5
XS GIS Cut Line= 5
1991671.00716985245831.7922600871991626.58930217245796.951323074
1991608.51766433245784.081720616 1991462.7186779245702.904262968
1991361.24685584245780.877347288
#Sta/Elev= 30
       0 1504.42    13.9 1502.96    24.5 1502.94    56.5 1501.01   108.2 1500.74
   128.2 1500.41   143.3 1499.16   158.3 1495.27   163.8 1492.68   166.1 1491.81
     177 1491.48   181.6  1492.8   187.8 1495.52   199.6 1496.51     214 1500.47
   220.7 1501.38   231.3 1500.62   240.9 1498.41   245.5 1498.11   254.6 1501.56
   267.6  1502.2   274.6 1506.64     277 1507.47   300.4 1507.24     303 1508.03
   308.4  1513.2   321.4 1527.97   352.1 1546.12   361.2 1552.98   373.5 1559.01
#Mann= 6 ,-1 , 0
       0     .04       0   108.2     .06       0   128.2     .04       0
   163.8    .045       0   181.6     .04       0   308.4      .1       0
#XS Ineff= 2 , 0
          159.49 1498.41  184.81         1498.41
Permanent Ineff=
       F       F
Bank Sta=163.8,181.6
XS Rating Curve= 0 ,0
Exp/Cntr(USF)=0,0
Exp/Cntr=0.5,0.3

Type RM Length L Ch R = 1 ,5       ,,,
XS GIS Cut Line= 5
1991676.02787069245759.3016368361991604.15135189245721.278705279
1991575.72608906245705.8186725541991441.89025127245677.803338564
1991390.62027801 245734.94799625
#Sta/Elev= 30
       0 1499.61    51.2 1500.02    58.6 1499.32    71.1 1499.15    83.2 1499.41
    87.6 1498.88    99.5  1493.3   108.2 1490.62     117 1489.46   127.8 1489.79
   130.7 1489.13   139.8 1488.83   151.9  1489.2   184.8 1492.46   197.1 1491.41
   214.9 1492.14     225 1493.46   238.4 1492.24   251.9 1492.48   259.1 1495.67
   265.1 1498.91   268.4 1500.04   282.7 1500.75   284.7  1502.1   291.6 1508.59
   295.9 1509.25   304.8 1508.87   313.6 1508.32   317.2 1508.66   327.2 1514.13
#Mann= 6 ,-1 , 0
       0     .04       0    71.1     .05       0   130.7    .045       0
   151.9     .05       0   259.1      .1       0   304.8     .04       0
Bank Sta=130.7,151.9
XS Rating Curve= 0 ,0
Exp/Cntr(USF)=0,0
Exp/Cntr=0.3,0.1
LCMann Table=0

Chan Stop Cuts=-1
Use User Specified Reach Order=0
Composite Channel Slope=5